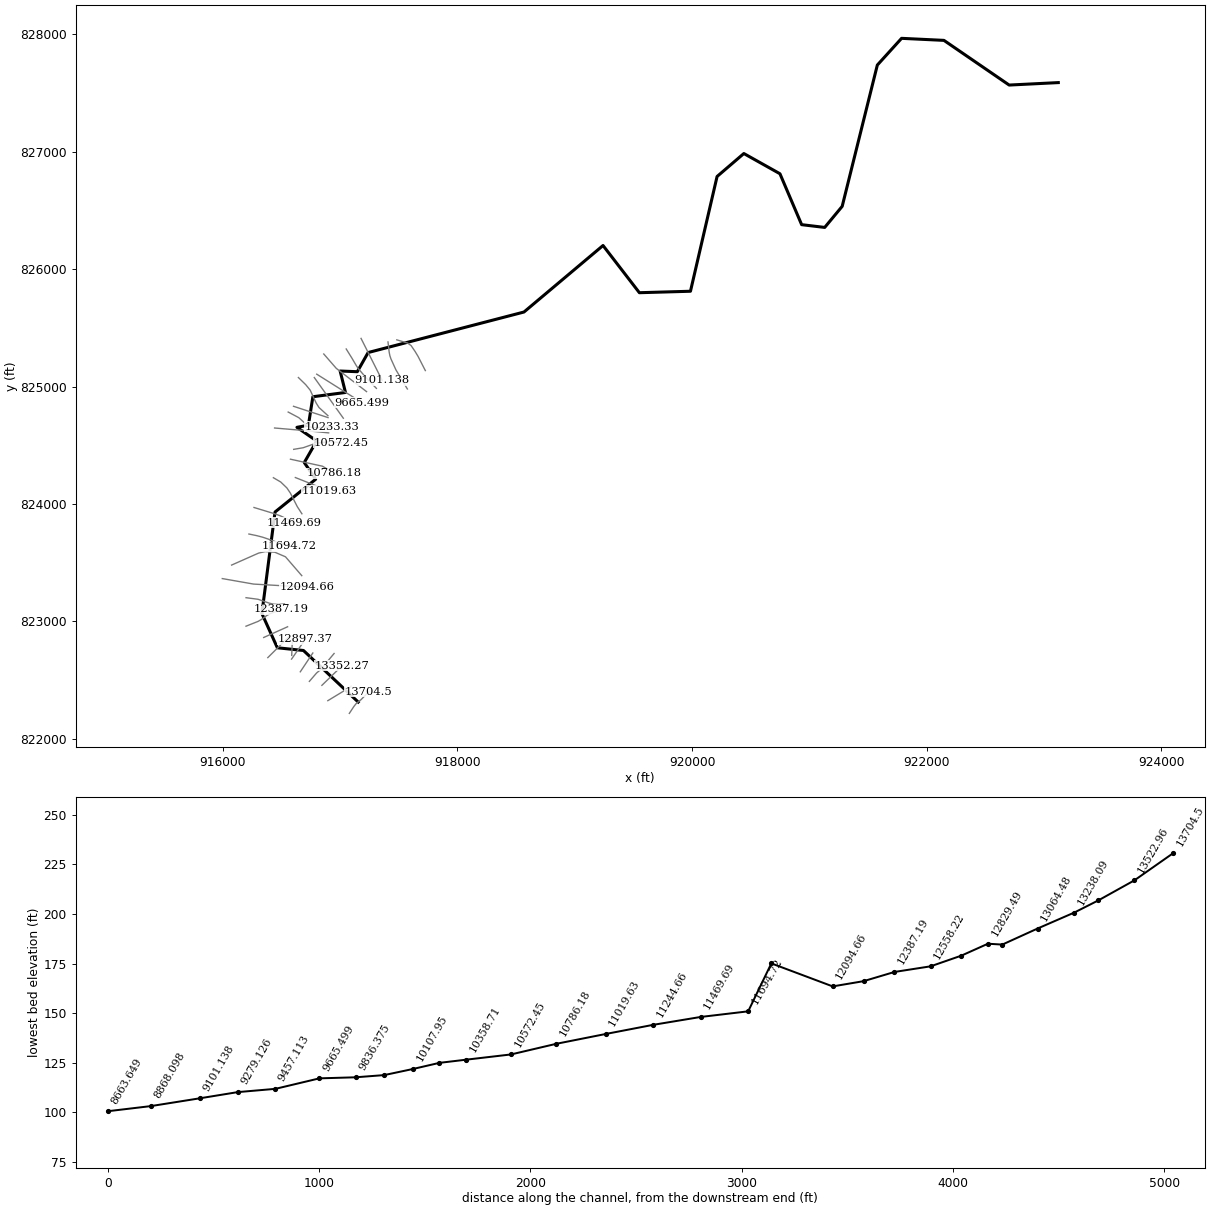
--- 16358_ras.prj (project) ---

Proj Title=16358
Current Plan=p01
Default Exp/Contr=0.3,0.1
English Units
Geom File=g01
Flow File=f01
Plan File=p01
Y Axis Title=Elevation
X Axis Title(PF)=Main Channel Distance
X Axis Title(XS)=Station
BEGIN DESCRIPTION:
RFD model 16358 exported to HEC-RAS
END DESCRIPTION:

--- 16358_ras.p01 (plan) ---

Plan Title=Plan 01
Program Version=4.10
Short Identifier=Plan 01
Geom File=g01
Flow File=f01
Subcritical Flow
Calc Critical at every XS
Secant Critical Depth

--- 16358_ras.f01 (steady flow) ---

Flow Title=Flow 01
Program Version=5.01
Number of Profiles= 6
Profile Names=10yr,25yr,50yr,100yr,100plus,500yr
River Rch & RM=16358,41, 13704.5
  306.09  457.11  590.19  700.07  1022.1 1519.83
River Rch & RM=16358,41,13522.96
  311.32  465.04  600.54  712.45 1040.18 1543.34
River Rch & RM=16358,41,13352.27
  312.74  467.19  603.35  715.82 1045.09 1549.73
River Rch & RM=16358,41,13064.48
  327.08  489.06  631.99  750.17 1095.26 1615.15
River Rch & RM=16358,41,12897.37
  328.91  491.85  635.66  754.57 1101.68 1623.51
River Rch & RM=16358,41,12829.49
  422.22   632.4  818.33  972.16 1419.35 2020.99
River Rch & RM=16358,41,12703.51
  424.85   636.4  823.57  978.45 1428.53 2032.47
River Rch & RM=16358,41,12558.22
   432.1  647.53   838.2  996.07 1454.26 2064.89
River Rch & RM=16358,41,12387.19
  436.13  653.81  846.54 1006.18 1469.03 2083.86
River Rch & RM=16358,41,12240.93
  437.32  655.67  849.02  1009.2 1473.44 2089.54
River Rch & RM=16358,41,12094.66
   449.2  674.25  873.74 1039.27 1517.34    2146
River Rch & RM=16358,41,11804.34
  474.11  713.11  925.39 1102.02 1608.96 2262.72
River Rch & RM=16358,41,11694.72
  475.28  714.94  927.83 1104.99 1613.28 2268.21
River Rch & RM=16358,41,11469.69
   478.8  720.43  935.13 1113.87 1626.25 2284.68
River Rch & RM=16358,41,11244.66
  531.49  802.79 1044.75 1247.21 1820.92 2529.88
River Rch & RM=16358,41,11019.63
  536.06  809.93 1054.25 1258.76 1837.78  2550.9
River Rch & RM=16358,41,10786.18
  545.86  825.26 1074.67 1283.62 1874.09 2596.23
River Rch & RM=16358,41,10572.45
  551.54  834.31 1086.84 1298.56  1895.9 2623.97
River Rch & RM=16358,41,10358.71
  553.93  838.15 1092.05    1305  1905.3 2636.07
River Rch & RM=16358,41,10107.95
  554.96   839.8 1094.28 1307.75 1909.32 2641.25
River Rch & RM=16358,41,9972.165
  555.64  840.89 1095.77 1309.59    1912  2644.7
River Rch & RM=16358,41,9836.375
  557.68  844.18 1100.23 1315.09 1920.04 2655.04
River Rch & RM=16358,41,9665.499
  564.71  855.38  1115.3 1333.62 1947.09 2689.39
River Rch & RM=16358,41,9457.113
  565.39  856.47 1116.78 1335.45 1949.76 2692.82
River Rch & RM=16358,41,9279.126
  566.41  858.11    1119 1338.19 1953.76 2697.95
River Rch & RM=16358,41,9101.138
  569.46  863.02 1125.66 1346.41 1965.76 2713.34
River Rch & RM=16358,41,8868.098
  575.56  872.83 1138.94 1362.82 1989.72    2744
River Rch & RM=16358,41,8663.649
  576.58  874.46 1141.16 1365.55 1993.71  2749.1
River Rch & RM=16358,41,8426.238
  591.77  898.88 1174.22 1406.38 2053.32 2825.13
River Rch & RM=16358,41,8208.945
  946.49 1452.36 1910.66 2301.56 3360.28 4365.85
River Rch & RM=16358,41,7935.936
  951.92 1461.11 1922.53 2316.24 3381.71 4391.32
River Rch & RM=16358,41,7702.896
  957.07 1469.38 1933.75  2330.1 3401.94 4415.32
River Rch & RM=16358,41,7469.855
  962.51 1478.13 1945.61 2344.76 3423.34 4440.68
River Rch & RM=16358,41,7236.815
  966.87 1485.22 1955.29 2356.79 3440.91 4461.76
River Rch & RM=16358,41,7003.774
  969.16 1488.95  1960.4 2363.16 3450.21 4472.99
Boundary for River Rch & Prof#=16358,41,1
Up Type= 0
Dn Type= 2
Boundary for River Rch & Prof#=16358,41,2
Up Type= 0
Dn Type= 2
Boundary for River Rch & Prof#=16358,41,2
Up Type= 0
Dn Type= 2
Boundary for River Rch & Prof#=16358,41,2
Up Type= 0
Dn Type= 2
Boundary for River Rch & Prof#=16358,41,2
Up Type= 0
Dn Type= 2
Boundary for River Rch & Prof#=16358,41,2
Up Type= 0
Dn Type= 2

--- 16358_ras.g01 (geometry) ---

Geom Title=16358
Program Version=4.10

River Reach=16358,41
Reach XY= 30
917154.307440877822313.244619191916687.632382363822752.489853442
916465.159683079822775.598015681916333.247743219823067.433359772
916445.184428066823931.744437352916791.396454006824210.552211717
916694.597368598824353.101855919 916799.89127627824536.835221902
916632.122749329824652.841085806916729.778999358824671.287266329
916767.793536633 824913.38249594917045.545882821824949.759590462
917000.145888358825132.370831057917146.409927726825126.600271285
917238.676568776825289.776849687918566.801568776825634.828932971
919240.629693776826201.235183001919550.446317077825799.310631692
919985.742701232825811.743575662920212.555692077826789.002471969
920440.728375524826984.553394616920748.362983704826812.331465006
920933.258817077826378.737715006 921129.87340036826355.300215036
921278.826909423826534.912319392921578.325367987827738.076546043
921784.922590226827965.507101581922146.033701301827948.145990491
922701.763608098827567.633809909923120.571415365827588.546184197

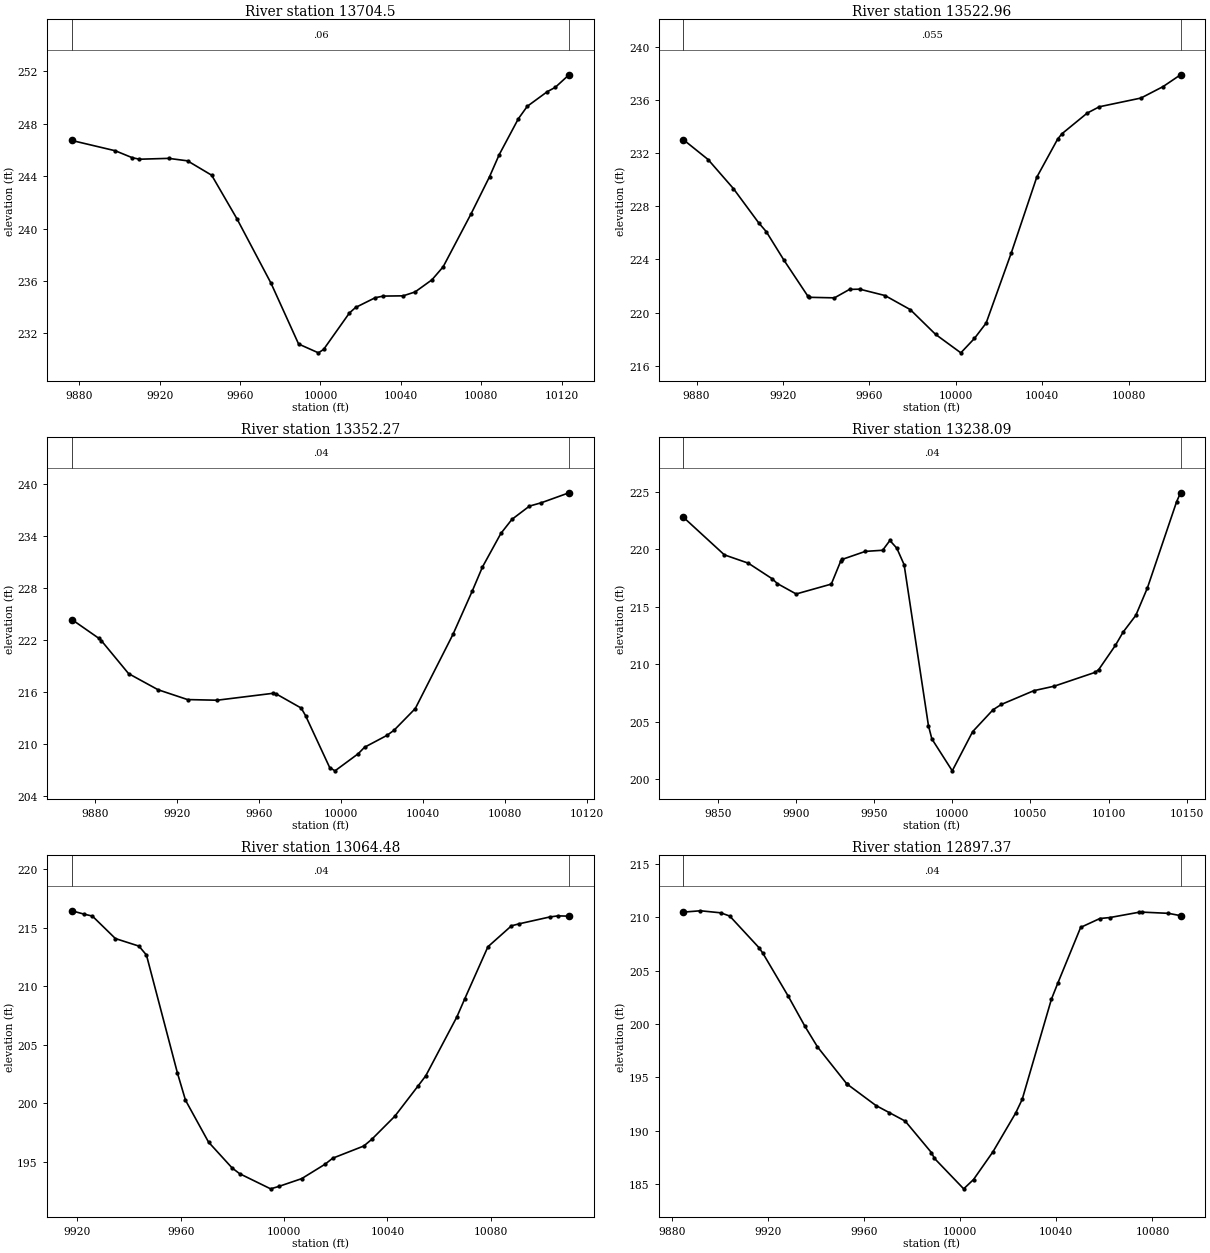
Type RM Length L Ch R = 1 , 13704.5,181.545200,181.545200,181.545200
XS GIS Cut Line= 6
917078.479455733822216.970163971917116.358746105822274.367911172
917133.878040312822297.167734267917144.349798358822307.168265252
917178.134115172822333.698231391917242.577196593822399.870435932
#Sta/Elev= 28
9876.329246.71949897.931245.93539906.322245.40979909.912245.28949924.477245.3546
9933.875245.16649945.896 244.0699958.507240.73429975.404235.83519989.142231.1913
    9999230.519110001.59230.7814 10014.4233.556310017.48233.979310027.27234.7255
 10031.3234.848310041.14234.867810047.08235.163310055.48236.090310061.04237.0792
10074.99241.138810084.14243.960510088.95245.642210098.48248.381810102.91249.3267
10112.81 250.43710116.87250.777810123.67251.7311
#Mann= 3 , 0 , 0
9876.329    0.06       09876.329    0.06       010123.67    0.06       0
#XS Ineff= 2 , 0
       0                               0
Bank Sta=9876.329,10123.67
Exp/Cntr=0.3,0.1

Type RM Length L Ch R = 1 ,13522.96,170.690400,170.690400,170.690400
XS GIS Cut Line= 2
916895.225203425822325.091558934917091.923820218 822444.51571913
#Sta/Elev= 26
9873.899233.02149885.335231.52819897.033229.34279908.732 226.763 9912.26226.0951
9920.431223.94949931.529221.2297 9932.13221.14779943.829221.10579950.797221.7426
9955.528221.75999967.226221.27999978.925220.21939990.624218.355510002.32216.9636
 10008.6218.047210014.02219.204910025.72224.518410037.42230.179710047.14233.0708
10049.12233.469810060.82235.027310066.41235.501110085.68236.158910095.91237.0206
10104.01237.9116
#Mann= 3 , 0 , 0
9873.899   0.055       09873.899   0.055       010104.01   0.055       0
#XS Ineff= 2 , 0
       0                               0
Bank Sta=9873.899,10104.01
Exp/Cntr=0.3,0.1

Type RM Length L Ch R = 1 ,13352.27,114.177200,114.177200,114.177200
XS GIS Cut Line= 2
916844.645559106 822455.75564009917018.864333981822624.354454484
#Sta/Elev= 26
9868.858224.33789882.151222.14559883.267221.89129896.531218.08629910.911216.2234
9925.291215.0889 9939.67215.01359966.763 215.807 9968.43215.75179980.679214.1106
 9982.81213.24119994.594207.23329997.189206.855810008.51208.832810011.57209.5778
10022.43210.940110025.95211.537910036.34214.052210054.71222.621910064.17227.6571
10069.09230.406110078.09234.287910083.47235.910110092.01237.439710097.85237.8302
 10111.3238.9785
#Mann= 3 , 0 , 0
9868.858    0.04       09868.858    0.04       0 10111.3    0.04       0
#XS Ineff= 2 , 0
       0                               0
Bank Sta=9868.858,10111.3
Exp/Cntr=0.3,0.1

Type RM Length L Ch R = 1 ,13238.09,173.613200,173.613200,173.613200
XS GIS Cut Line= 4
 916737.86630999822489.475402969916799.685875268822561.129899086
916832.000648027822587.824711365916948.614827983822726.918733241
#Sta/Elev= 30
9828.006222.78159854.235219.50599869.544218.78299884.852217.42269888.132217.0069
9900.161 216.1029922.642216.96169928.719218.97959929.535219.10869944.421219.8087
9955.477219.90629960.122220.75679964.557220.08599969.226218.64969984.791204.6366
 9986.97203.487810000.02200.707510013.07204.118210026.12206.024810031.49206.4906
10052.22207.685510065.27208.076710091.37 209.27710093.75209.526610104.42211.6358
10109.31212.779110117.46214.243210124.88216.634810143.56224.136410146.07224.9097
#Mann= 3 , 0 , 0
9828.006    0.04       09828.006    0.04       010146.07    0.04       0
#XS Ineff= 2 , 0
       0                               0
Bank Sta=9828.006,10146.07
Exp/Cntr=0.3,0.1

Type RM Length L Ch R = 1 ,13064.48,167.108100,167.108100,167.108100
XS GIS Cut Line= 2
916660.591853392822570.964829926916767.371102509822731.133703601
#Sta/Elev= 29
9917.836216.46229922.685216.16669925.782216.00969934.704214.0847 9943.81213.4388
9946.722212.67529958.741  202.569961.838  200.259970.759196.66389979.866194.4566
9982.778193.96239994.796192.66349997.893192.863810006.81193.534510015.92194.7771
10018.83195.285410030.85 196.32710033.95196.899310042.87198.874110051.98201.4965
10054.89202.347210066.91207.3779   10070 208.94810078.93213.383110088.03215.1735
10090.94215.342610102.96215.936710106.06216.025810110.33216.0039
#Mann= 3 , 0 , 0
9917.836    0.04       09917.836    0.04       010110.33    0.04       0
#XS Ineff= 2 , 0
       0                               0
Bank Sta=9917.836,10110.33
Exp/Cntr=0.3,0.1

Type RM Length L Ch R = 1 ,12897.37,67.882600,67.882600,67.882600
XS GIS Cut Line= 2
916586.127377035822679.149069162916704.146547111822849.152873677
#Sta/Elev= 30
9884.765210.49449891.888210.61939900.324210.42779904.061210.12529916.235207.1636
 9917.86206.63889928.408202.61939935.395199.78219940.582197.86869952.755 194.414
9952.931194.37689964.929192.37229970.466191.70929977.102190.91259988.002187.9671
9989.276187.419610001.45184.565510005.54185.436410013.62188.034510023.07191.6625
 10025.8192.947810037.97202.336510040.61203.829910050.14209.063810058.14209.8939
10062.32209.986510074.49210.484910075.68210.493610086.66210.379610091.72 210.162
#Mann= 3 , 0 , 0
9884.765    0.04       09884.765    0.04       010091.72    0.04       0
#XS Ineff= 2 , 0
       0                               0
Bank Sta=9884.765,10091.72
Exp/Cntr=0.3,0.1

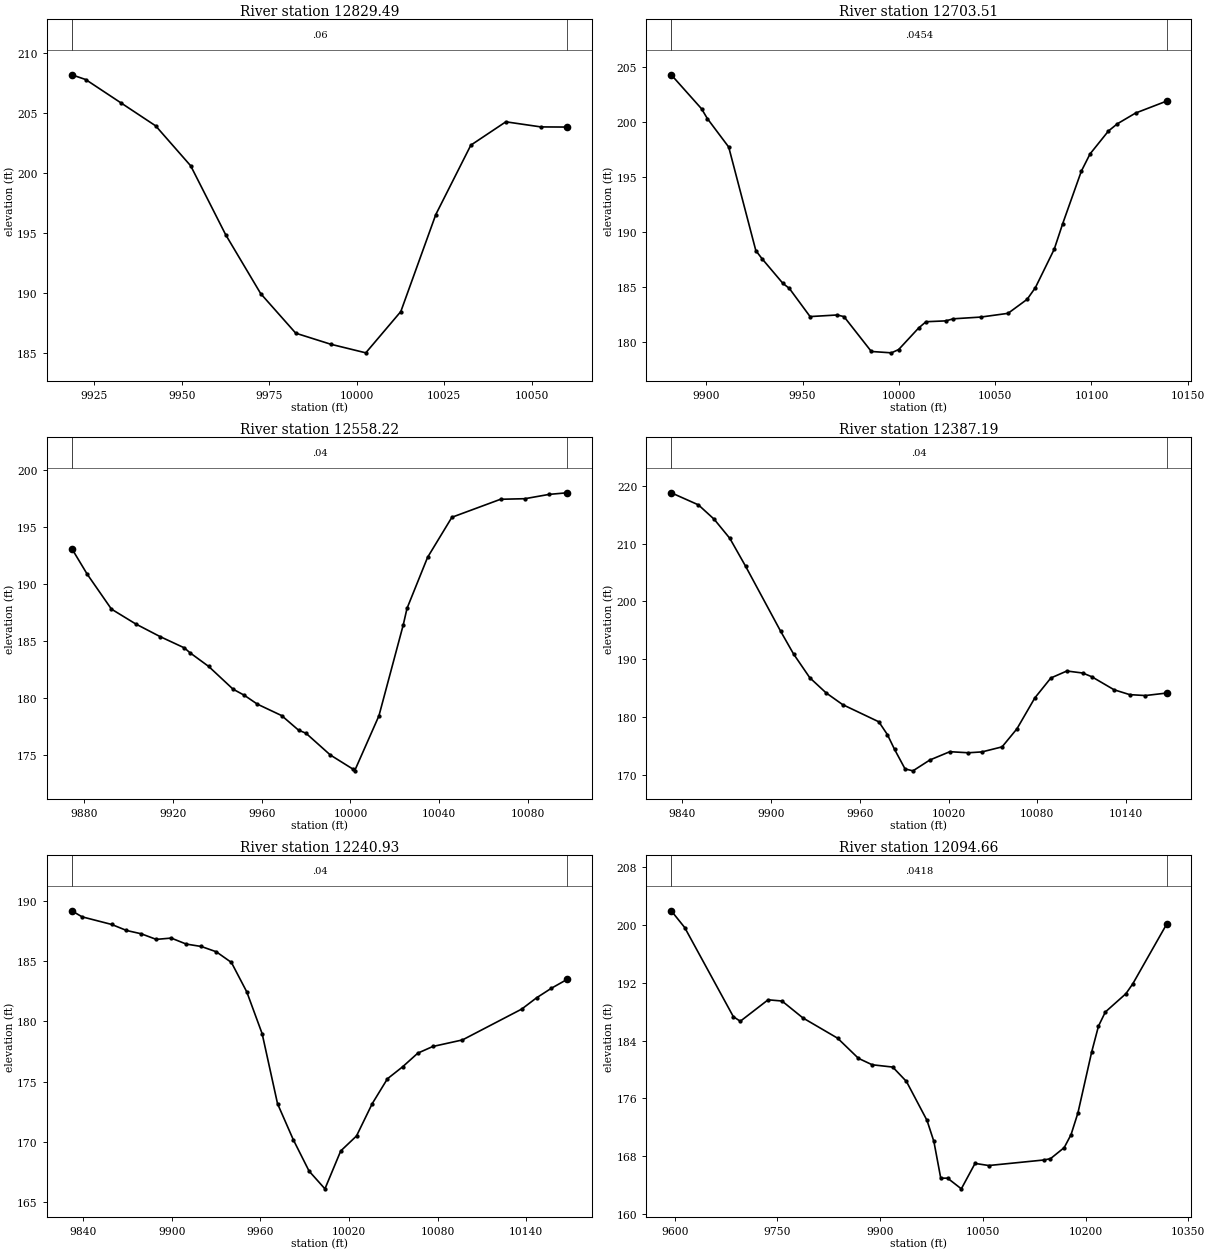
Type RM Length L Ch R = 1 ,12829.49,125.972600,125.972600,125.972600
XS GIS Cut Line= 2
 916587.51527366822711.030521095916593.212707609822852.516798452
#Sta/Elev= 16
 9918.58208.20599922.553  207.819932.561205.87719942.569203.94239952.577200.6081
9962.585194.85169972.593189.93849982.602186.6401 9992.61185.717910002.62185.0002
10012.63188.446310022.63196.543310032.64202.331310042.65204.280710052.66203.8549
10060.18203.8422
#Mann= 3 , 0 , 0
 9918.58    0.06       0 9918.58    0.06       010060.18    0.06       0
#XS Ineff= 2 , 0
       0                               0
Bank Sta=9918.58,10060.18
Exp/Cntr=0.3,0.1

Type RM Length L Ch R = 1 ,12703.51,145.289600,145.289600,145.289600
XS GIS Cut Line= 2
916383.808799761822691.793980242916566.457515356822873.037705716
#Sta/Elev= 30
9881.781 204.2949897.547201.1965 9900.53200.31199911.635197.71749925.723188.2933
9928.924187.55879939.811 185.3059943.121184.85349953.899182.28849967.987182.4349
9971.515182.28349985.712179.11269996.162178.98889999.909179.289610010.25181.2454
10014.11181.820910024.34 181.897 10028.3182.0863 10042.5182.2431 10056.7182.5834
 10066.6183.856110070.89184.915110080.69188.415910085.09190.742110094.78195.5222
10099.29197.089210108.87199.179710113.49199.833810122.95200.810910139.09201.8998
#Mann= 3 , 0 , 0
9881.781  0.0454       09881.781  0.0454       010139.09  0.0454       0
#XS Ineff= 2 , 0
       0                               0
Bank Sta=9881.781,10139.09
Exp/Cntr=0.3,0.1

Type RM Length L Ch R = 1 ,12558.22,171.033800,171.033800,171.033800
XS GIS Cut Line= 2
916348.684046763822863.202774876916552.407614156822954.527132673
#Sta/Elev= 26
9874.437193.12989881.359190.88949892.317 187.8129903.276186.50739914.235185.3996
9925.194184.40749927.724183.97829936.153 182.7789947.111180.7857 9952.17180.2514
 9958.07179.47069969.029178.46429976.617177.18949979.988176.91619990.947175.0083
10001.06173.778910001.91173.615910012.86178.446810023.82186.428810025.51187.8728
10034.78192.354410045.74195.872210067.66197.451610078.62197.501810089.58197.8811
10097.69198.0216
#Mann= 3 , 0 , 0
9874.437    0.04       09874.437    0.04       010097.69    0.04       0
#XS Ineff= 2 , 0
       0                               0
Bank Sta=9874.437,10097.69
Exp/Cntr=0.3,0.1

Type RM Length L Ch R = 1 ,12387.19,146.264200,146.264200,146.264200
XS GIS Cut Line= 6
916197.745624325 822959.26496518916301.607625721 823000.63839584
916331.091018891823017.919231031916375.910098167823051.145333714
916403.844802599823066.244982499916498.544642088823101.660779607
#Sta/Elev= 30
9832.625218.76189850.977216.67699861.612214.20199872.248210.88499882.884206.0783
 9906.48194.89569915.312 190.9299926.283186.82819937.254184.22959948.435182.2029
9972.905179.23249978.678177.02859983.533174.47059990.614171.10219995.955170.7713
10007.38172.643710020.88174.076210033.34173.889610042.58174.039110056.17174.9087
10066.22178.0289 10078.3183.356910089.12186.795510099.94188.001510110.66187.6535
10116.79187.010510131.84184.763510142.43183.921210153.02 183.76710167.37184.1966
#Mann= 3 , 0 , 0
9832.625    0.04       09832.625    0.04       010167.37    0.04       0
#XS Ineff= 2 , 0
       0                               0
Bank Sta=9832.625,10167.37
Exp/Cntr=0.3,0.1

Type RM Length L Ch R = 1 ,12240.93,146.264200,146.264200,146.264200
XS GIS Cut Line= 6
916198.070204897823202.172890657916300.811655949823188.540043612
916393.826508271823156.330311583916431.009687964823147.298248458
916474.689021958823144.386537541916525.639211194823149.209959669
#Sta/Elev= 29
9832.212189.17379839.168188.67369859.241188.04059869.278 187.5439879.315187.2651
9889.416186.80349899.577186.91079909.738186.41449919.899186.21629930.061185.7772
9940.326 184.8929950.737182.45199961.148178.98459971.559173.18619982.209170.2077
9992.925167.601410003.66166.130710014.35169.271310025.04170.512710035.69173.1921
10045.98175.251410056.27176.245310066.56 177.37710076.75177.928810096.79178.4714
10136.92181.028110146.97181.961810157.01182.7533 10167.7183.4917
#Mann= 3 , 0 , 0
9832.212    0.04       09832.212    0.04       0 10167.7    0.04       0
#XS Ineff= 2 , 0
       0                               0
Bank Sta=9832.212,10167.7
Exp/Cntr=0.3,0.1

Type RM Length L Ch R = 1 ,12094.66,290.323700,290.323700,290.323700
XS GIS Cut Line= 3
915995.644289001823364.877891594916263.005400112823318.002891594
916714.394289001823291.961224928
#Sta/Elev= 30
9594.926201.96359614.577199.64869685.645187.31529695.797186.67759736.408189.6459
9756.713189.4799 9787.17187.14499837.933184.33569868.363181.54849888.397180.6606
9918.447 180.339 9938.48178.3466 9968.53 172.9549978.546170.04489988.563164.9744
 9998.58164.969610018.61163.493910038.65167.011810058.68166.719510138.81167.4823
10148.83167.665910168.86169.197110178.88170.9969 10188.9173.996410208.93182.4064
10218.95186.014510228.96187.961410259.01190.495510269.03191.8578 10318.5200.1143
#Mann= 3 , 0 , 0
9594.926  0.0418       09594.926  0.0418       0 10318.5  0.0418       0
#XS Ineff= 2 , 0
       0                               0
Bank Sta=9594.926,10318.5
Exp/Cntr=0.3,0.1

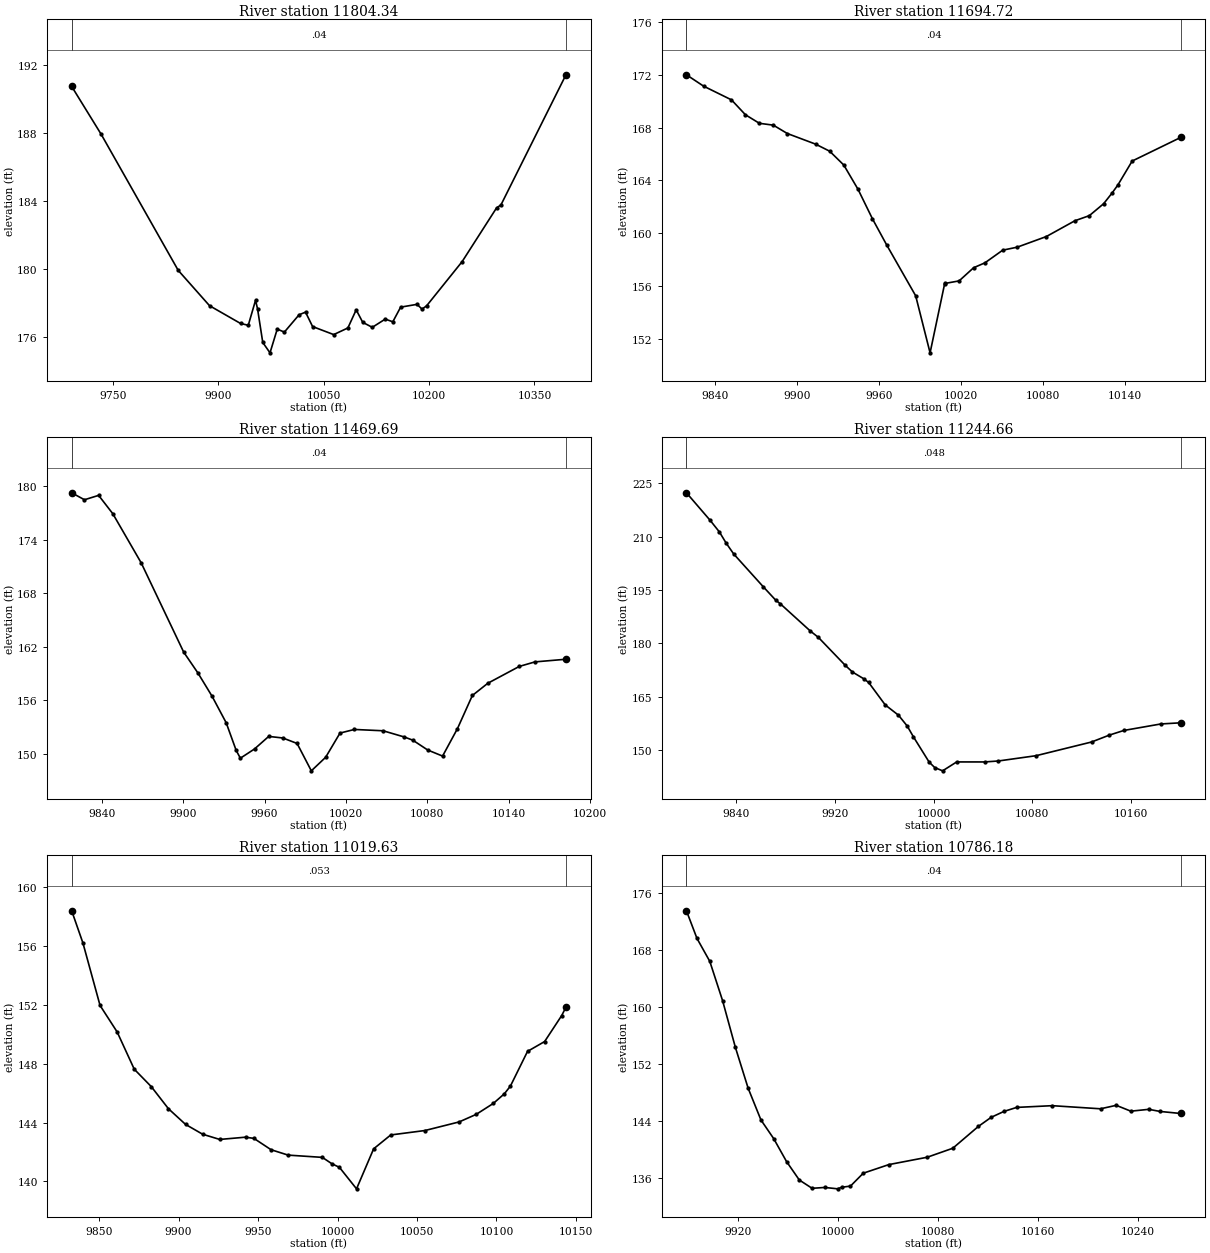
Type RM Length L Ch R = 1 ,11804.34,109.622000,109.622000,109.622000
XS GIS Cut Line= 6
916075.288386223823479.895252706916305.323108445823581.891780483
916361.746719556823594.912613817 916443.12692789823589.487266594
916534.272761223823550.424766594916673.161650112823389.834488817
#Sta/Elev= 30
9690.993190.72239732.904187.91959842.682179.92919887.293177.85429931.454 176.812
9942.483176.70519952.814178.16979955.655177.67839963.122175.69659973.429175.0873
9983.729176.47899993.903176.304910014.87 177.32310024.05177.475310034.08176.6295
10064.17176.158210084.35 176.54810096.17177.6115 10105.5176.877110119.08176.5844
10137.56177.067210148.33176.909510159.48177.769510182.86177.933710189.92177.6547
 10196.4177.843710247.11180.444110296.01183.588910302.39183.772710394.93191.4072
#Mann= 3 , 0 , 0
9690.993    0.04       09690.993    0.04       010394.93    0.04       0
#XS Ineff= 2 , 0
       0                               0
Bank Sta=9690.993,10394.93
Exp/Cntr=0.3,0.1

Type RM Length L Ch R = 1 ,11694.72,225.028200,225.028200,225.028200
XS GIS Cut Line= 6
916222.703743766823744.352806624916290.685768545823730.136516033
916340.475096149823717.068618103916398.378548354823697.568852397
916479.961446712823667.749170687916568.944597698823640.126541529
#Sta/Elev= 30
9818.973 172.0129831.535171.15039851.968170.10989862.184 168.981  9872.4168.3324
9882.617168.19259892.886167.55819913.563166.75429923.902166.21669934.241165.1686
9944.676163.3264 9955.23161.09089965.783159.08459986.889155.25539997.443150.9283
10008.05156.136810008.48156.1926 10018.7 156.38310029.34157.381710037.61 157.752
10050.64158.712610061.29158.940810082.58159.745210103.61160.948110114.08161.3294
10124.55162.232810130.87163.059610135.02163.657310145.49165.471910181.03167.2609
#Mann= 3 , 0 , 0
9818.973    0.04       09818.973    0.04       010181.03    0.04       0
#XS Ineff= 2 , 0
       09914.422                       0
Bank Sta=9818.973,10181.03
Exp/Cntr=0.3,0.1

Type RM Length L Ch R = 1 ,11469.69,225.028200,225.028200,225.028200
XS GIS Cut Line= 6
916265.998371728823970.285029324916422.977867829823922.562253143
916441.234241132823916.659297433 916487.49396818823900.407191431
916548.100922661823872.908548183916604.700128343823839.711723281
#Sta/Elev= 30
 9817.74179.24879827.148178.4661  9837.6178.95859848.052176.90359868.956171.4039
9900.311161.39499910.763159.06679921.215 156.4569931.667153.47049939.051150.3677
9942.119149.50349952.571150.54029963.023151.94549973.432151.76799983.938151.1567
9994.444148.086910004.99149.603710015.59152.319510026.19152.724710047.39152.5763
10063.12151.874210069.26151.523110080.24150.422310091.22149.7409 10102.2152.8206
10113.18156.531910124.58 157.90210147.77159.787910159.36160.2963 10182.2160.5934
#Mann= 3 , 0 , 0
 9817.74    0.04       0 9817.74    0.04       0 10182.2    0.04       0
#XS Ineff= 2 , 0
       09974.375                       0
Bank Sta=9817.74,10182.2
Exp/Cntr=0.3,0.1

Type RM Length L Ch R = 1 ,11244.66,225.028200,225.028200,225.028200
XS GIS Cut Line= 6
916431.265075697824223.835548482916493.843287209824187.245353996
916546.250752202824136.781564899 916575.91292858 824093.07467711
916634.611236927823978.012673337 916674.24273996823916.772713173
#Sta/Elev= 30
9799.792222.3262 9818.98 214.586 9826.53211.29639831.939208.18779838.111205.1058
9861.857195.96239872.356192.03299875.826191.11279900.104183.46219906.736181.6391
9928.366173.82489934.283171.91179943.405170.02229947.439168.97229960.866162.6555
 9971.61159.76169978.674156.72659983.695153.68799996.482146.5525   10001145.0313
10007.36144.110610018.77146.616910041.38146.611910052.54146.883410083.13148.3717
10128.05152.221910142.51 154.16810154.19 155.46810184.18 157.29610200.29157.6223
#Mann= 3 , 0 , 0
9799.792   0.048       09799.792   0.048       010200.29   0.048       0
#XS Ineff= 2 , 0
       0                               0
Bank Sta=9799.792,10200.29
Exp/Cntr=0.3,0.1

Type RM Length L Ch R = 1 ,11019.63,233.450900,233.450900,233.450900
XS GIS Cut Line= 2
916618.414860684824225.307929548916907.477360684824110.724596214
#Sta/Elev= 30
9832.765  158.419839.849156.21279850.606151.96959861.363150.1653 9872.12147.6327
9882.877146.44179893.634144.94319904.391143.87729915.148143.20769925.905142.8535
9942.149143.00769947.419142.92449958.176142.15469968.933 141.7879990.447141.6333
9996.423141.2018 10001.2140.954610011.96139.492810022.72 142.21510033.48143.1585
10054.99143.4602 10076.5144.044810087.26144.559910098.02145.304110104.97 145.961
10108.77146.484310119.53148.843710130.29149.513910141.05151.285210143.71151.8524
#Mann= 3 , 0 , 0
9832.765   0.053       09832.765   0.053       010143.71   0.053       0
#XS Ineff= 2 , 0
       0                               0
Bank Sta=9832.765,10143.71
Exp/Cntr=0.3,0.1

Type RM Length L Ch R = 1 ,10786.18,213.733500,213.733500,213.733500
XS GIS Cut Line= 3
916576.748194018824381.557929548916850.185694018824321.662096214
916949.144027351824261.766262881
#Sta/Elev= 30
9878.968173.49099887.416169.61549897.653166.4132 9907.89160.91269918.127 154.374
9928.364148.63919938.601144.19879948.838141.57659959.076138.37829969.313 135.788
 9979.55134.62599989.787134.746810000.02134.551910003.09134.767910010.26 134.937
 10020.5136.741610040.97137.946210071.68138.976610092.16140.237210112.63143.2946
10122.87144.567710133.11145.394610143.29145.956310171.76146.197710210.38145.7611
10222.96146.247310234.65145.4275   10249145.685310258.03145.390610274.56145.1037
#Mann= 3 , 0 , 0
9878.968    0.04       09878.968    0.04       010274.56    0.04       0
#XS Ineff= 2 , 0
       0                               0
Bank Sta=9878.968,10274.56
Exp/Cntr=0.3,0.1

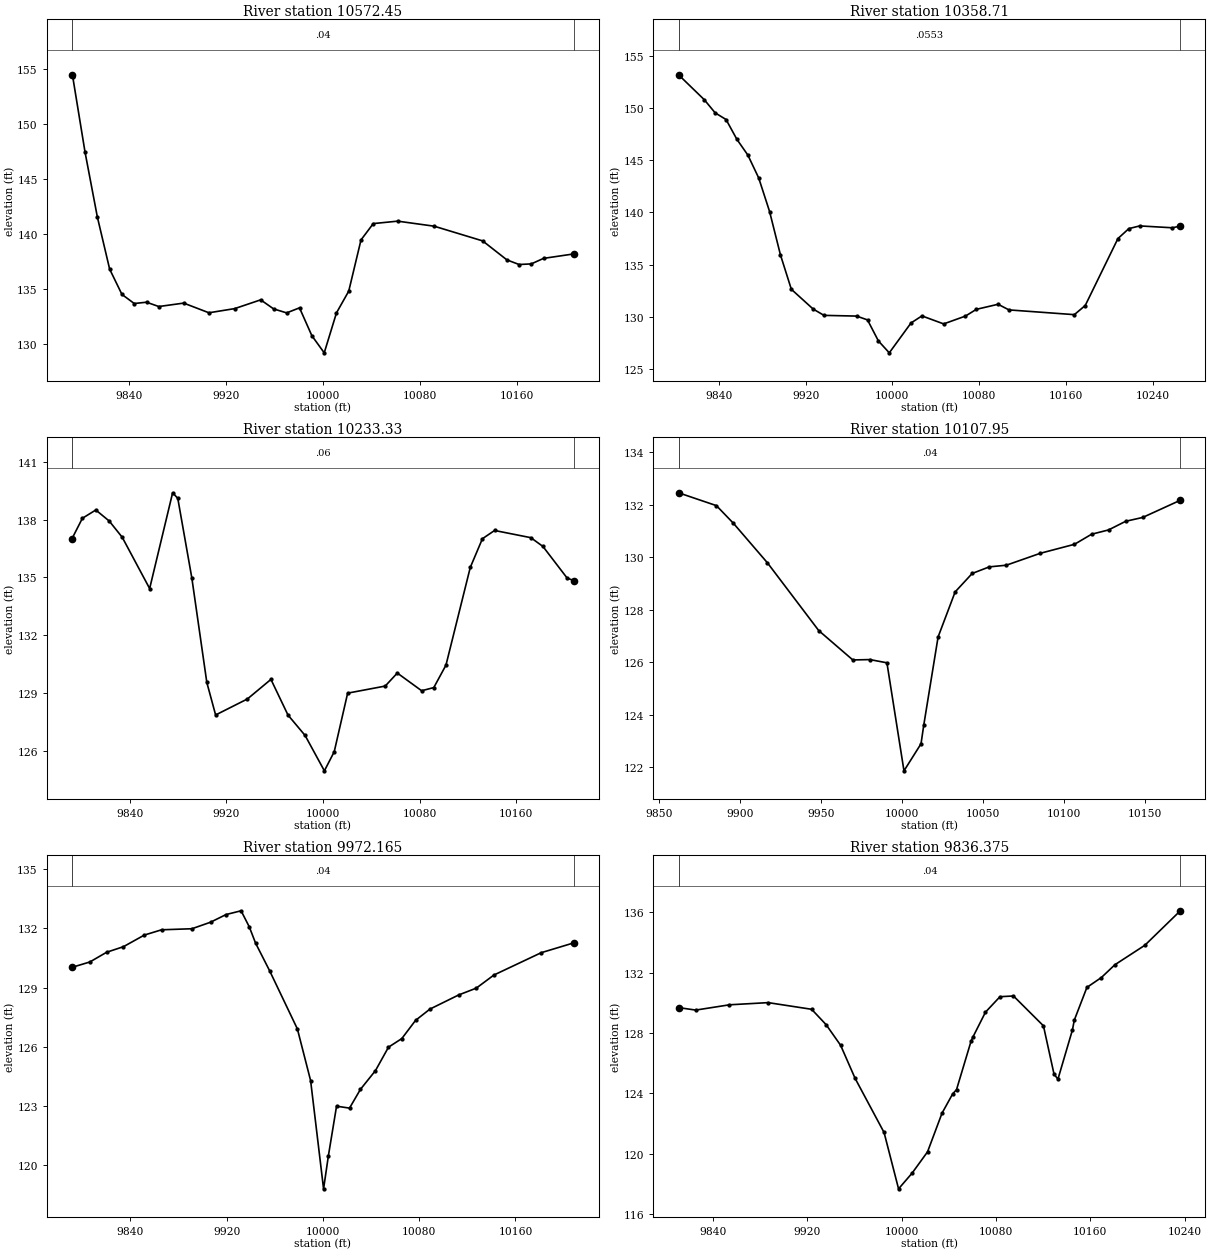
Type RM Length L Ch R = 1 ,10572.45,213.733600,213.733600,213.733600
XS GIS Cut Line= 6
916604.422694762824465.352279652916685.792258147824479.317129704
916782.616044294824513.473431515916848.657999167824524.864729087
916923.783361183  824530.2562524917009.821287955824521.944258072
#Sta/Elev= 30
9792.902154.43639793.488154.22949803.634147.4002 9813.78 141.5289823.927136.7992
9834.073134.50449844.219133.67929854.365133.79699864.511133.40459885.054133.7161
9905.888 132.8389927.152133.21629948.602134.01199959.327133.18849970.052132.8282
9980.656133.28689990.873130.755910001.07129.202710011.19 132.83210021.31134.8029
10031.43139.449510041.55140.9318 10061.7141.153210091.83140.695310131.86139.3606
10151.88137.637610161.91137.2193   10172137.2732 10182.1137.774610207.15138.1805
#Mann= 3 , 0 , 0
9792.902    0.04       09792.902    0.04       010207.15    0.04       0
#XS Ineff= 2 , 0
       0                               0
Bank Sta=9792.902,10207.15
Exp/Cntr=0.3,0.1

Type RM Length L Ch R = 1 ,10358.71,125.379000,125.379000,125.379000
XS GIS Cut Line= 3
916441.331527351824647.182929548916746.019027351824621.141262881
916902.269027351824605.516262881
#Sta/Elev= 30
9802.766153.1774 9826.52150.78919836.557 149.5299846.593148.8915 9856.63146.9861
9866.666145.49219876.703 143.2979886.739140.07849896.776135.92339906.812132.6297
9926.885130.74119936.921130.13139967.031130.06269977.067129.69649987.104127.6833
 9997.14126.542210017.21129.403510027.25130.079910047.32129.3137 10067.4130.0635
10077.43 130.708 10097.5131.194410107.54130.654710167.84130.200310177.89131.0767
10208.04137.488410218.09138.441210228.14138.700410258.29138.521510265.59138.6873
#Mann= 3 , 0 , 0
9802.766  0.0553       09802.766  0.0553       010265.59  0.0553       0
#XS Ineff= 2 , 0
       0                               0
Bank Sta=9802.766,10265.59
Exp/Cntr=0.3,0.1

Type RM Length L Ch R = 1 ,10233.33,125.379000,125.379000,125.379000
XS GIS Cut Line= 6
916557.302718057824783.122792716916647.705138156824735.196872475
916721.603196459824668.741851698916751.384396115824653.455240496
916781.295328739824649.322493262916930.524258944 824657.28041515
#Sta/Elev= 30
9792.047137.01779800.599138.06939811.711138.49939822.822137.92779833.618137.0826
9856.343134.42049875.384139.39349879.655139.10629891.311134.96749903.725129.5438
9911.018127.85599937.355128.68729956.856129.70359971.012127.85039985.168126.7927
10001.16124.955610009.31125.947310020.43128.989210051.57129.3573 10061.6130.0329
10081.75129.114610091.83129.278910101.91130.442910122.06135.516810132.13137.0081
10142.21137.436110172.24137.062310182.28136.606910202.36134.963110207.91134.8334
#Mann= 3 , 0 , 0
9792.047    0.06       09792.047    0.06       010207.91    0.06       0
#XS Ineff= 2 , 0
       0                               0
Bank Sta=9792.047,10207.91
Exp/Cntr=0.3,0.1

Type RM Length L Ch R = 1 ,10107.95,135.789700,135.789700,135.789700
XS GIS Cut Line= 2
916602.789860684824832.078762881916897.060694018824735.724596214
#Sta/Elev= 23
9862.174132.45559885.544131.96629896.067131.29179917.058129.78599948.679127.2083
9969.723126.08899980.246 126.1039990.768125.980110001.29121.865810011.81122.8964
10013.47123.596610022.34126.964710032.86  128.6810043.38129.3824 10053.9129.6333
10064.43129.696810085.47130.152310106.51130.493210117.04130.876310127.56131.0411
10138.08131.3692 10148.6131.516210171.82132.1709
#Mann= 3 , 0 , 0
9862.174    0.04       09862.174    0.04       010171.82    0.04       0
#XS Ineff= 2 , 0
       0                               0
Bank Sta=9862.174,10171.82
Exp/Cntr=0.3,0.1

Type RM Length L Ch R = 1 ,9972.165,135.789600,135.789600,135.789600
XS GIS Cut Line= 6
916644.431980839 825076.94787302916706.750049541825016.202428229
916744.848883558824969.568411465916795.980827016824859.576061548
916819.946202668824821.493382261916896.110798895824752.274137426
#Sta/Elev= 30
9791.435130.02449806.193130.29539820.158130.78889834.122131.07089851.531131.6609
9865.857 131.9289891.052131.98149906.527132.3124 9919.41132.7006 9931.92132.8923
9938.715132.0795    9944131.24699955.568129.85919978.703126.90149989.701124.2835
10000.48118.790110004.51120.475310011.27122.982210022.06 122.884 10031.1123.8336
10043.64124.788110054.44125.974610065.51126.410610076.92127.3326 10088.9127.9064
10112.76128.622510127.43128.9696 10142.1129.634710181.41130.766910208.52131.2661
#Mann= 3 , 0 , 0
9791.435    0.04       09791.435    0.04       010208.52    0.04       0
#XS Ineff= 2 , 0
       0                               0
Bank Sta=9791.435,10208.52
Exp/Cntr=0.3,0.1

Type RM Length L Ch R = 1 ,9836.375,170.876200,170.876200,170.876200
XS GIS Cut Line= 2
916779.873194018825076.870429548917027.269027351824730.516262881
#Sta/Elev= 30
9810.716129.69339825.303129.52749853.945129.87829886.748130.02239923.615129.5802
9935.904128.56149948.193127.19499960.483125.00299985.061121.4146 9997.35117.6804
10008.79 118.71710021.93120.131910034.22122.6972 10043.2123.966910046.51124.2552
10058.79127.4506 10060.4127.737910071.08129.391210083.37130.414410094.81130.4629
10120.24128.483710129.22125.283610132.53124.948610144.82128.208110146.42 128.862
10157.11131.0309 10169.4131.686210180.83132.531710206.26133.823510236.35136.1095
#Mann= 3 , 0 , 0
9810.716    0.04       09810.716    0.04       010236.35    0.04       0
#XS Ineff= 2 , 0
       0                               0
Bank Sta=9810.716,10236.35
Exp/Cntr=0.3,0.1

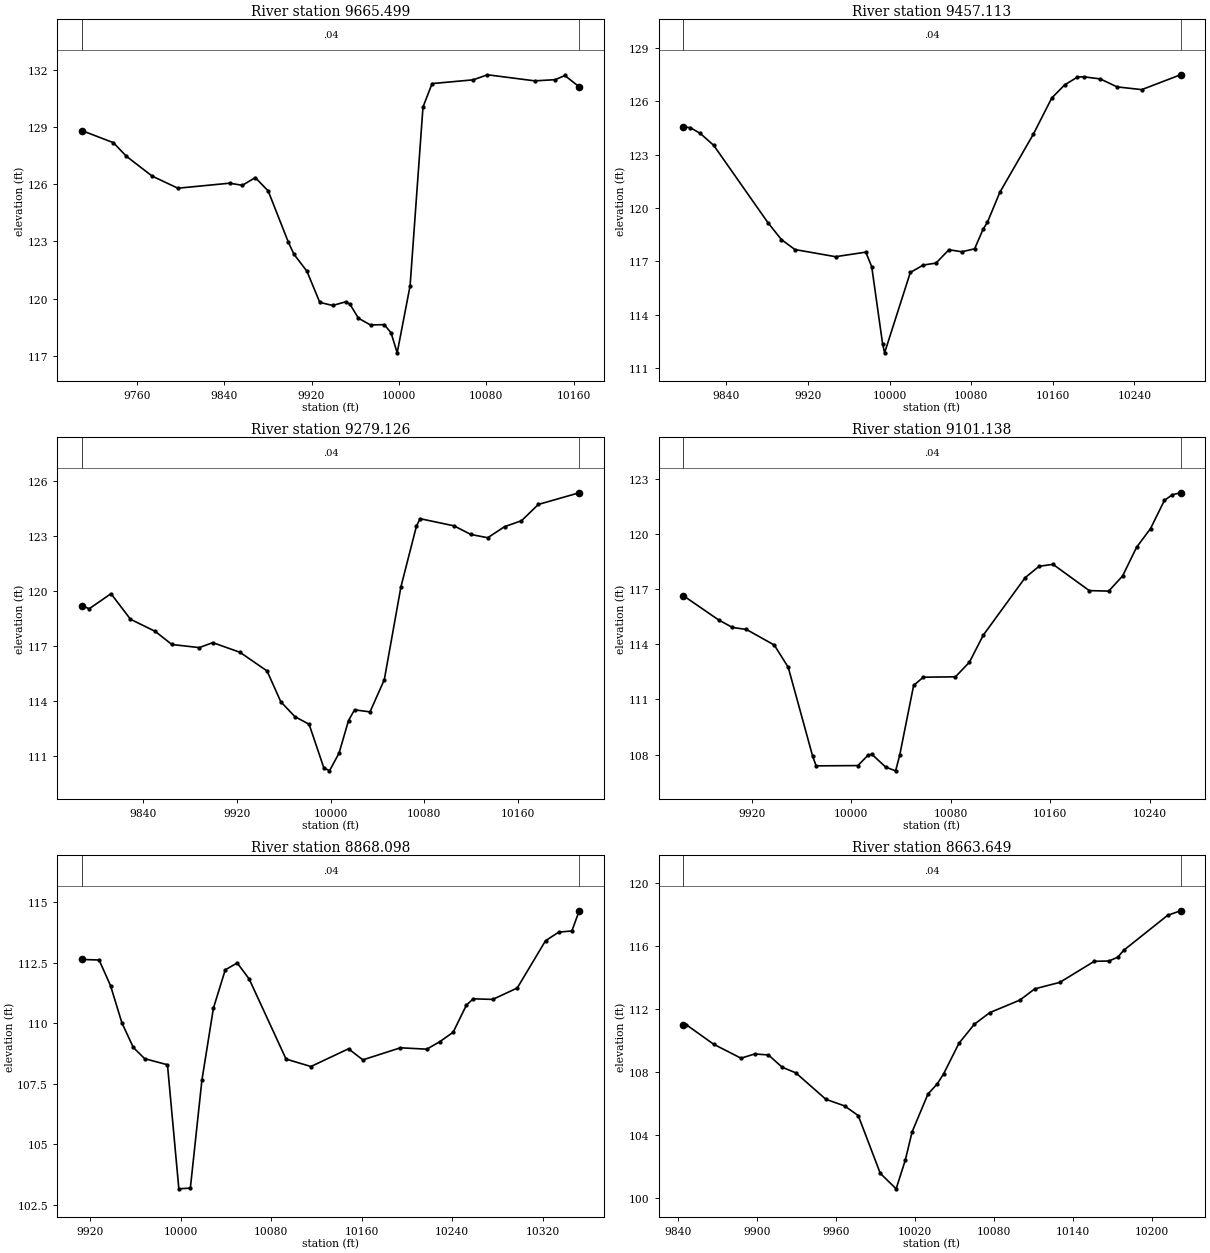
Type RM Length L Ch R = 1 ,9665.499,208.385800,208.385800,208.385800
XS GIS Cut Line= 2
916800.706527351825105.516262881917186.123194018824863.328762881
#Sta/Elev= 30
9709.897128.82039738.588128.18919750.399127.4784 9774.02126.4342 9797.64125.7978
9844.882  126.069856.693125.95099868.503126.35639880.313125.65229898.818122.9512
9903.934122.32579915.745121.43839927.555   119.89939.365119.63569951.176119.8286
9955.203119.69859962.986118.96559973.998118.61239986.607118.63189992.793   118.2
9998.418117.148610010.23120.671810022.04 130.06310030.38131.293710067.97131.4908
10081.09131.756510124.36131.437210143.15 131.49910151.95 131.71910165.09131.1202
#Mann= 3 , 0 , 0
9709.897    0.04       09709.897    0.04       010165.09    0.04       0
#XS Ineff= 2 , 0
       0                               0
Bank Sta=9709.897,10165.09
Exp/Cntr=0.3,0.1

Type RM Length L Ch R = 1 ,9457.113,177.987600,177.987600,177.987600
XS GIS Cut Line= 3
916860.602360684825277.391262881916967.373194018825154.995429548
917225.185694018824957.078762881
#Sta/Elev= 30
9797.916124.55159804.606124.5122 9814.36124.1905 9827.63 123.5169880.711119.1781
9893.981118.22269907.251117.66329947.062117.26139976.753117.5173 9982.56 116.692
9993.175112.37359995.167  111.8610020.38116.373610032.99 116.79210045.59116.9019
 10058.2117.651710070.81117.539410083.41117.702710091.71118.800910096.02119.2005
10108.13120.875310140.97124.137810159.06126.176810171.66126.910710184.27127.3531
10190.24127.369210206.66 127.24910223.08 126.801 10247.3126.647410285.36127.4817
#Mann= 3 , 0 , 0
9797.916    0.04       09797.916    0.04       010285.36    0.04       0
#XS Ineff= 2 , 0
       0                               0
Bank Sta=9797.916,10285.36
Exp/Cntr=0.3,0.1

Type RM Length L Ch R = 1 ,9279.126,177.987600,177.987600,177.987600
XS GIS Cut Line= 6
917051.941132739825320.126488171  917100.0159554825242.871635438
917138.453793706825177.430842065917156.953037952 825150.31653765
 917216.81908624825080.523772245917309.235302296824984.545814457
#Sta/Elev= 30
9787.552 119.221 9793.59119.04219812.269119.86559828.925118.47259850.123117.8106
9864.259117.09839887.673116.92819899.271 117.1999922.465116.6744 9945.66115.6559
9957.381113.97919969.487113.16619981.593112.75259994.109110.3923    9999110.2162
 10007.2111.183510015.28112.957610020.42113.539110033.64 113.42810045.86115.1781
10060.08120.2401 10073.3123.537110076.44123.951610105.43123.560610119.85123.0919
10134.26122.913510148.68123.5171 10163.1123.837510177.52124.726710212.46 125.362
#Mann= 3 , 0 , 0
9787.552    0.04       09787.552    0.04       010212.46    0.04       0
#XS Ineff= 2 , 0
       0                               0
Bank Sta=9787.552,10212.46
Exp/Cntr=0.3,0.1

Type RM Length L Ch R = 1 ,9101.138,233.040400,233.040400,233.040400
XS GIS Cut Line= 2
917178.310694018825410.203762881917357.998194018825053.432929548
#Sta/Elev= 30
9865.207116.63639893.427115.32469904.624114.91419915.821 114.8059938.214113.9573
9949.411112.75169969.003107.92939971.804107.394210005.39107.409310013.47107.9696
10016.59108.023710027.79107.3243 10035.7107.123610038.98107.969110050.18111.7628
10057.93112.211510083.77112.231410094.97113.022710106.16114.495610139.75117.6161
10150.95118.234910162.15118.343710191.31116.915710206.94116.888410218.13117.7151
10229.33119.270610240.53 120.28510251.72121.819210258.01122.121710264.67122.2306
#Mann= 3 , 0 , 0
9865.207    0.04       09865.207    0.04       010264.67    0.04       0
#XS Ineff= 2 , 0
       09910.982        10154.15       0
Bank Sta=9865.207,10264.67
Exp/Cntr=0.3,0.1

Type RM Length L Ch R = 1 ,8868.098,204.448400,204.448400,204.448400
XS GIS Cut Line= 6
917407.990076566825379.956730299917418.152924767825292.450772328
917424.041890848825262.602527473917433.282589555825235.247081842
917475.739493433825142.015615496917573.154944819824979.447886812
#Sta/Elev= 30
9912.906112.63339927.962112.61139938.029111.55539948.096110.01839958.163109.0049
 9968.23108.53999988.363 108.289 9998.43103.170510008.59103.201610018.79107.6441
10028.98110.625710039.45112.2045   10050112.490710060.57111.828110093.19108.5234
10115.13108.216910148.37108.947810161.05108.491910194.26108.989610217.57108.9328
10229.23109.245910240.89 109.63310252.55110.7492 10258.6111.010310275.86 110.986
10297.51 111.456 10322.5113.406710334.15113.760210345.81113.811410352.28114.6423
#Mann= 3 , 0 , 0
9912.906    0.04       09912.906    0.04       010352.28    0.04       0
#XS Ineff= 2 , 0
       09913.374        10045.83       0
Bank Sta=9912.906,10352.28
Exp/Cntr=0.3,0.1

Type RM Length L Ch R = 1 ,8663.649,237.411600,237.411600,237.411600
XS GIS Cut Line= 6
917482.963685501825397.899427734917575.138024733825370.700442387
917604.952846168825348.886571004917638.735005969825299.160462912
917663.840630621825257.640697903917726.227247991825136.143950799
#Sta/Elev= 30
9843.751 110.9999845.874111.00319866.727109.76199887.579108.87329898.006109.1431
9908.432109.08059918.858108.30099929.285107.94169952.074106.26739966.444105.8396
9976.797105.22449993.528101.560310005.61100.574810012.54102.388710017.74104.1895
10029.85106.601410036.92107.241810041.78 107.88610053.46109.828110065.15111.0322
10076.84 111.76710099.78112.565310111.12113.279610130.22113.692310156.34115.0276
 10167.5115.048110174.23115.288310178.67115.721310212.15117.947310222.03118.2385
#Mann= 3 , 0 , 0
9843.751    0.04       09843.751    0.04       010222.03    0.04       0
#XS Ineff= 2 , 0
       09867.947                       0
Bank Sta=9843.751,10222.03
Exp/Cntr=0.3,0.1