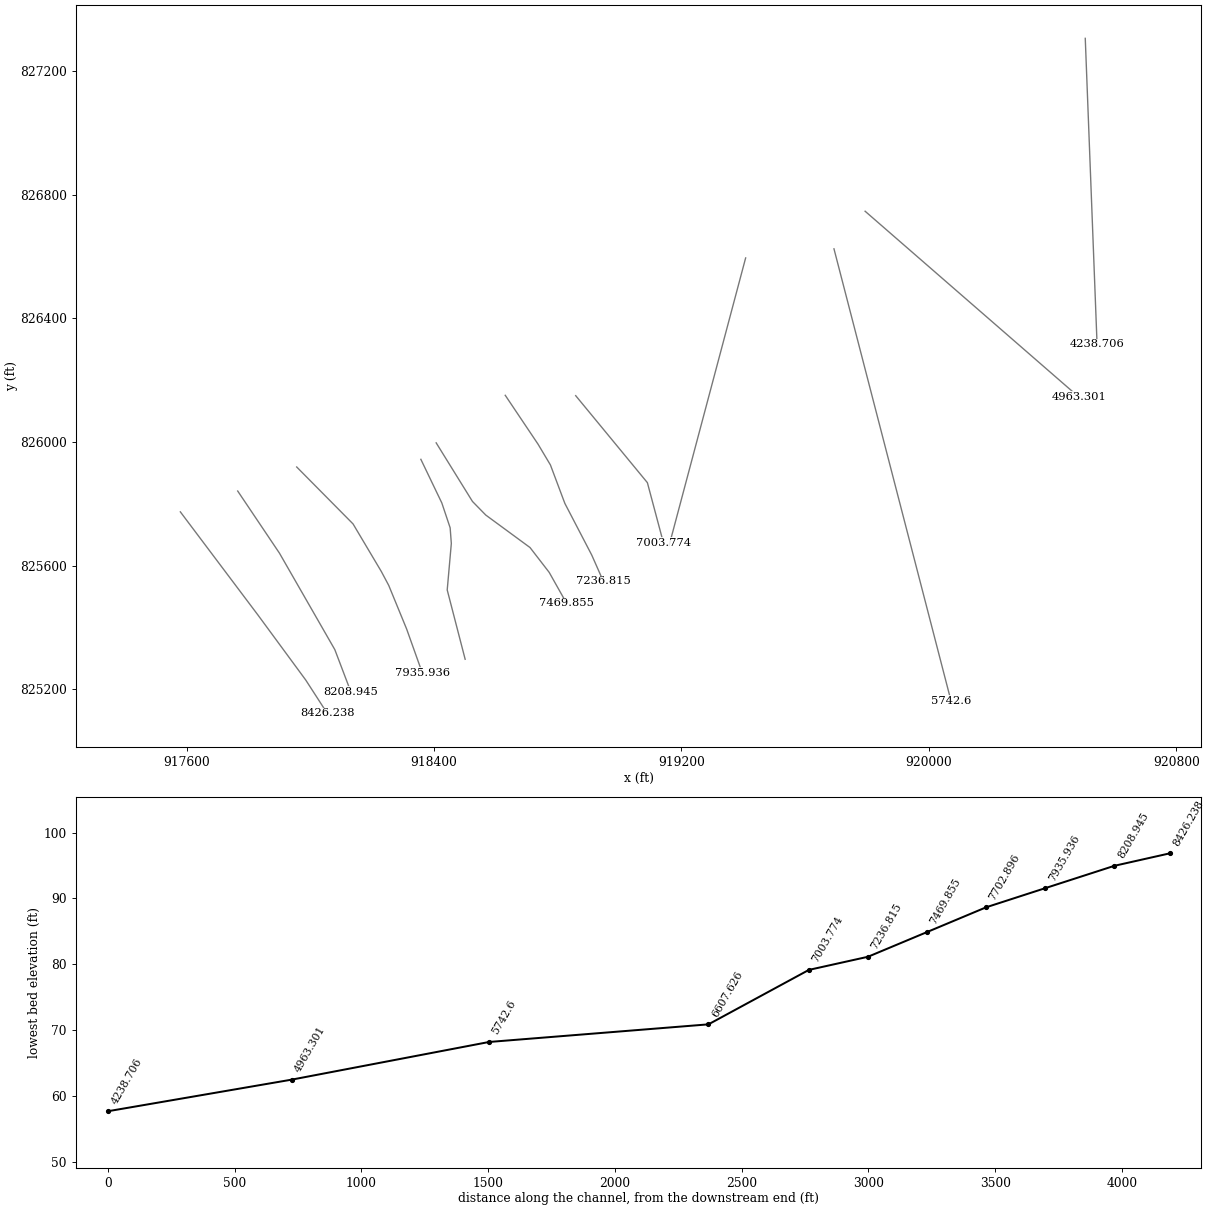
HEC-RAS study 16358_ras.prj: 16358

--- 16358_ras.g01 (geometry) --- (continued)

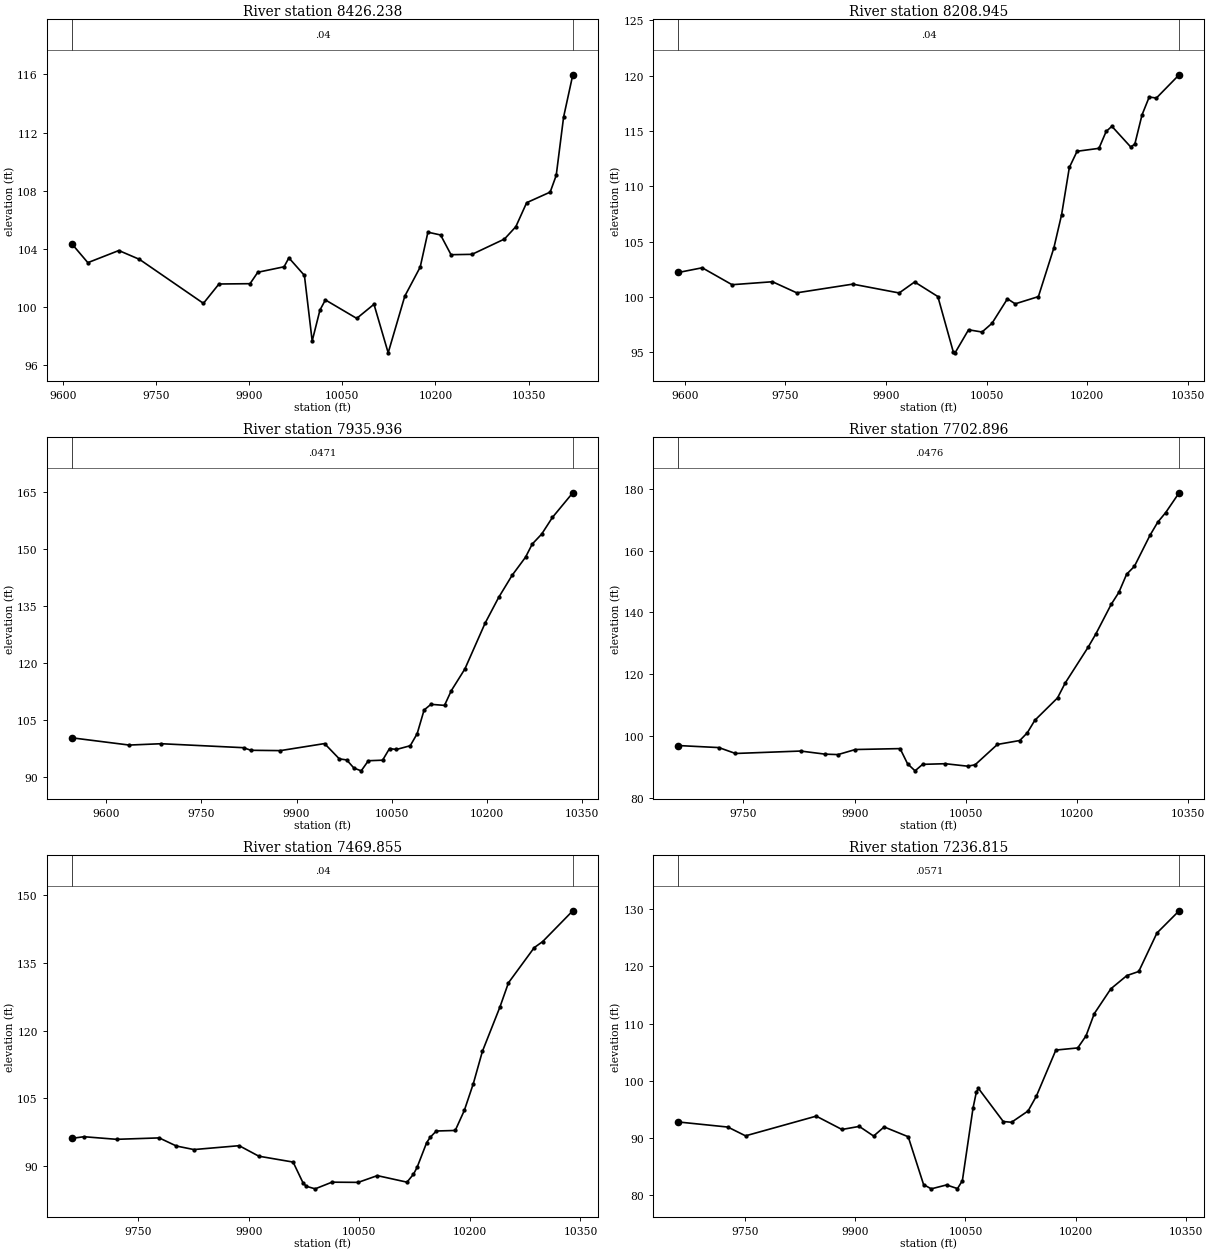
Type RM Length L Ch R = 1 ,8426.238,217.292400,217.292400,217.292400
XS GIS Cut Line= 4
917579.671188957825774.152058367917830.825551122825440.260186492
917985.245781385825230.193026404918054.783884456825122.551853159
#Sta/Elev= 30
 9614.65104.3315 9640.15103.05089690.056 103.8859723.327103.27759826.314100.2527
 9851.34101.58349901.393101.60459913.906  102.399956.223102.76729963.959103.3806
9988.986102.1738 10001.597.6635110014.0199.7913810022.77100.488810073.2799.21847
10101.04100.189510123.9296.8498410150.69100.748210175.51102.746910187.92105.1456
10208.34104.953710225.15103.597910258.99 103.62310311.26104.676110329.58105.5266
10346.98107.174110384.86107.9021 10394.6109.0521 10406.5113.066510421.32115.9695
#Mann= 3 , 0 , 0
 9614.65    0.04       0 9614.65    0.04       010421.32    0.04       0
#XS Ineff= 2 , 0
       09972.003         10079.4       0
Bank Sta=9614.65,10421.32
Exp/Cntr=0.3,0.1

Type RM Length L Ch R = 1 ,8208.945,273.009300,273.009300,273.009300
XS GIS Cut Line= 4
917765.166329701825841.427053479917900.210452823825640.487906424
918079.197502842 825328.60029232918130.628218589825193.266645818
#Sta/Elev= 30
9590.546 102.2289626.104 102.6539670.581 101.1249730.824101.3917 9766.97100.3905
9850.506101.17589919.684100.37739942.743101.37219977.333100.054110000.3995.04433
   1000394.9674410023.0997.0505710043.1896.8487210058.0497.63396 10081.199.85197
10092.6399.3948510127.22100.048310150.28104.451710161.81107.451810173.34111.7165
10184.87113.179610217.49113.445510228.19114.971310236.73115.437810264.88113.5654
10270.98113.837510281.68116.467410292.38118.082610303.08 117.98910337.02120.0919
#Mann= 3 , 0 , 0
9590.546    0.04       09590.546    0.04       010337.02    0.04       0
#XS Ineff= 2 , 0
       09933.021                       0
Bank Sta=9590.546,10337.02
Exp/Cntr=0.3,0.1

Type RM Length L Ch R = 1 ,7935.936,233.040400,233.040400,233.040400
XS GIS Cut Line= 6
 917955.92381959825919.213313551918138.138084509825735.061034515
918229.468332769825581.407012757918253.458366534825536.327326736
918311.446971998825395.091855104918361.513542432825254.706463352
#Sta/Elev= 30
9545.576100.26979635.91198.364039686.43898.718129816.34497.669979827.977 96.9868
 9874.5196.899539944.30898.756149967.57594.726789979.20894.44436 9990.6892.29649
10002.1691.5689810013.4394.2344210035.9294.3764810046.8397.4456910057.7597.20193
10079.5998.1898210090.51101.372510101.43107.603710112.24109.099310133.68108.8244
 10144.4112.705910165.84118.430610197.76130.498310219.13137.273510240.36143.1014
 10261.6147.893610272.21  151.3610287.07153.980710304.06158.378410336.23164.8712
#Mann= 3 , 0 , 0
9545.576  0.0471       09545.576  0.0471       010336.23  0.0471       0
#XS Ineff= 2 , 0
       0 9936.97                       0
Bank Sta=9545.576,10336.23
Exp/Cntr=0.3,0.1

Type RM Length L Ch R = 1 ,7702.896,233.040500,233.040500,233.040500
XS GIS Cut Line= 6
918357.359688349825943.955734925918425.137322004825802.882897899
918452.054368204825722.560672235918455.858027957 825671.86614154
918442.563527585825521.631018198 918500.57058322 825297.53339335
#Sta/Elev= 30
9662.14896.855589716.85496.195749739.20394.287079827.14495.073879860.24294.06653
9877.566 93.92789900.95795.569469961.34995.866579971.41490.953199981.52788.66161
 9991.7490.7644310022.38 90.969910052.5890.1671310062.5890.6227210092.6397.21376
10122.8798.4893310132.99100.986110143.12105.029610173.77 112.28310184.04117.0792
   10215128.6889 10225.4132.974310246.19142.595810256.59146.5095   10267152.3518
 10277.5 154.91310298.52164.964310309.03169.235110319.74172.339410337.89178.7495
#Mann= 3 , 0 , 0
9662.148  0.0476       09662.148  0.0476       010337.89  0.0476       0
#XS Ineff= 2 , 0
       09890.059                       0
Bank Sta=9662.148,10337.89
Exp/Cntr=0.3,0.1

Type RM Length L Ch R = 1 ,7469.855,233.040400,233.040400,233.040400
XS GIS Cut Line= 6
918406.854201477825997.261195396918524.220094324825807.760404283
918567.263731264 825763.74752834918710.304063156825658.771572831
918772.261306087825578.504981025918828.493651721825478.616426164
#Sta/Elev= 30
9660.34696.102969676.56596.463749720.78395.887159778.60596.202399801.88194.40301
9825.667 93.61429887.08694.474569913.74592.143919960.242 90.83839973.84386.17576
 9978.2585.460459990.16984.9001810012.9686.3792710048.5186.3345310074.4787.83162
10114.6986.3815910123.4788.1338610128.3989.6491510141.4595.1700110146.3396.35957
10154.5197.73096 10180.297.8534110192.47102.291510204.73108.261210216.99115.3953
10240.69125.199510252.35130.612910287.32138.419110298.73139.754110339.64146.5936
#Mann= 3 , 0 , 0
9660.346    0.04       09660.346    0.04       010339.64    0.04       0
#XS Ineff= 2 , 0
       09851.391                       0
Bank Sta=9660.346,10339.64
Exp/Cntr=0.3,0.1

Type RM Length L Ch R = 1 ,7236.815,233.040400,233.040400,233.040400
XS GIS Cut Line= 6
918630.218263963826150.990073376918736.354386229  825992.7686396
918776.247433995825925.858108744918822.907572322825801.531183685
918909.926274507825634.323627579918947.248125816825549.897252789
#Sta/Elev= 30
9658.87992.826059726.29991.938489750.38390.403979846.71593.847529881.73191.51628
9905.33992.052469924.86690.367999939.22991.960279972.01890.245339992.985 81.8795
10003.4381.14419 10024.381.8263510039.1481.18593 10045.882.5743610060.3295.26453
10064.8598.0466710067.6898.69545 10101.592.9078410112.7792.7757810135.3294.74896
10146.5997.3323410173.16105.391210202.96105.762910214.23107.8642 10225.5111.7564
10248.05116.091810269.94 118.40910286.09119.119210310.83125.834910341.12129.7257
#Mann= 3 , 0 , 0
9658.879  0.0571       09658.879  0.0571       010341.12  0.0571       0
#XS Ineff= 2 , 0
       09822.343                       0
Bank Sta=9658.879,10341.12
Exp/Cntr=0.3,0.1

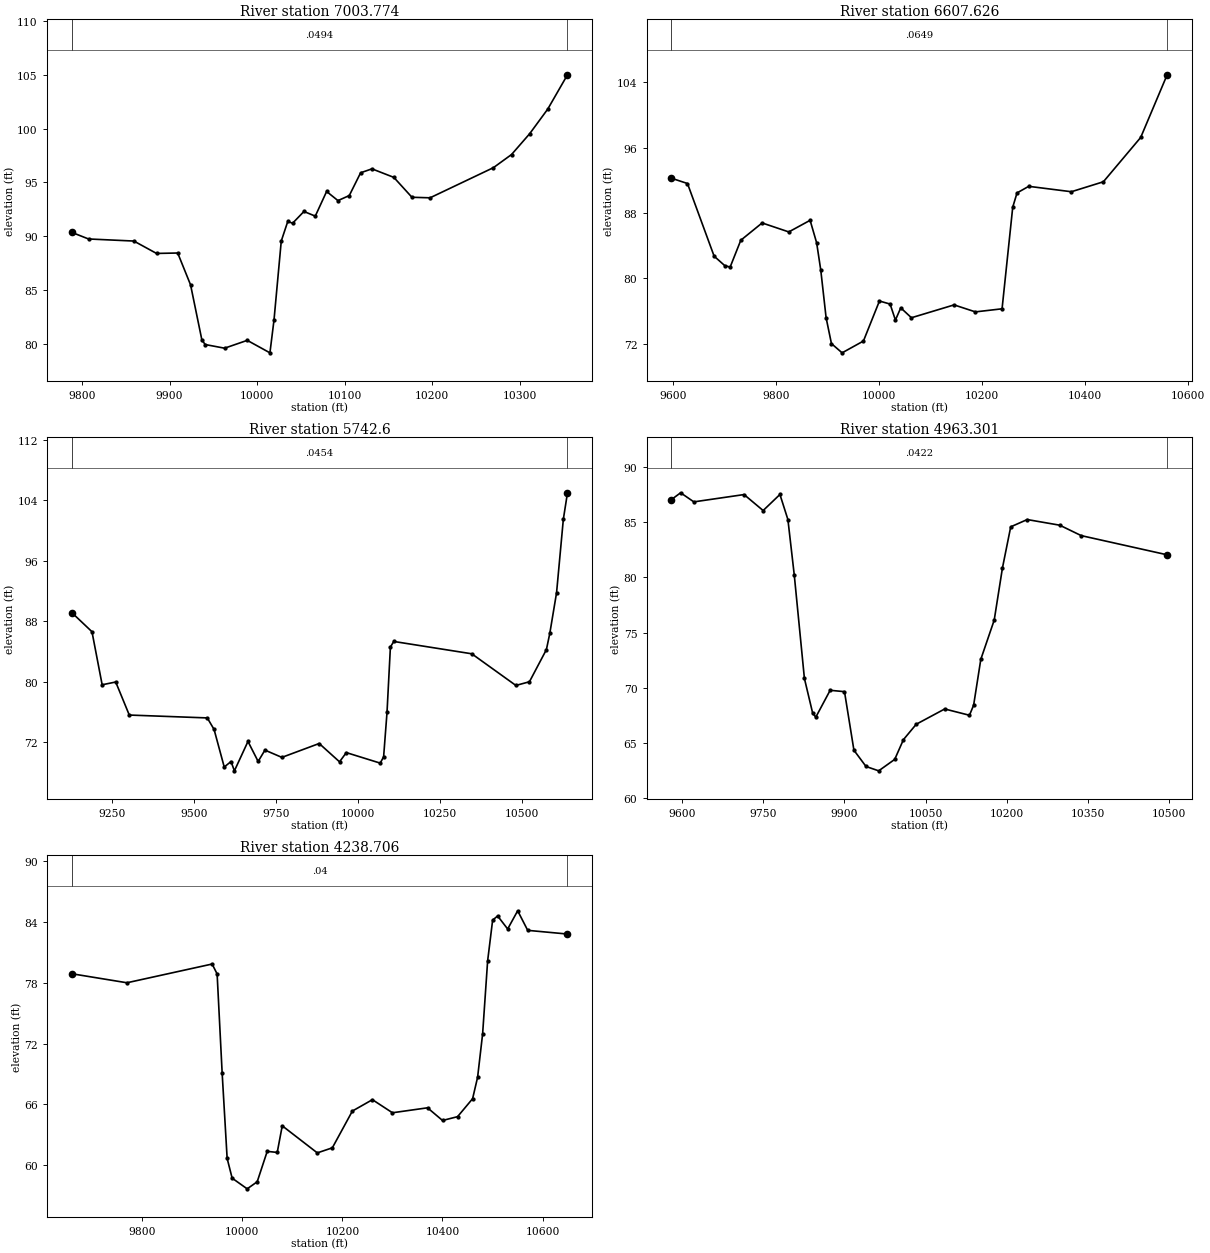
Type RM Length L Ch R = 1 ,7003.774,396.148100,396.148100,396.148100
XS GIS Cut Line= 3
918857.998194018826149.787096214919089.769027351825868.537096214
919141.852360684825673.224596214
#Sta/Elev= 30
9788.15790.349699807.31889.73673 9859.1589.542839885.06688.391199909.23788.43094
 9923.9485.469879936.89880.338379940.68579.921949962.814 79.5816 9988.7380.31087
10014.6579.1498910019.3182.20431 10027.689.5430110035.0391.3648710040.5691.20012
10053.5292.2920610066.4891.8606810079.4494.1521210092.39 93.303410105.3593.77284
10118.3195.8905110131.2796.2553910156.2695.4630910176.9693.6130310197.6693.56271
10270.1196.36695 10290.897.58699 10311.599.51886 10332.2101.813710354.74105.0015
#Mann= 3 , 0 , 0
9788.157  0.0494       09788.157  0.0494       010354.74  0.0494       0
#XS Ineff= 2 , 0
       09824.456                       0
Bank Sta=9788.157,10354.74
Exp/Cntr=0.3,0.1

Type RM Length L Ch R = 1 ,6607.626,865.026300,865.026300,865.026300
XS GIS Cut Line= 2
919407.477360684826595.099596214919160.081527351825665.412096214
#Sta/Elev= 30
9597.04592.249639628.19291.602199679.93282.704139700.62881.546869710.976 81.3718
9731.67284.656489773.06586.775099824.80585.676219866.19787.097949878.88684.33655
9886.89380.994829897.24175.168069907.589  72.0059928.28570.875569969.67772.32027
10000.7277.2174510021.4276.8470910031.7674.8871110042.1176.3842910062.81 75.1707
10145.5976.7439610186.9875.8879510238.7276.2658510259.4288.7049810267.7590.45083
10290.46 91.257210373.2590.5959410435.3491.8142710507.7797.2405710559.09104.9114
#Mann= 3 , 0 , 0
9597.045  0.0649       09597.045  0.0649       010559.09  0.0649       0
#XS Ineff= 2 , 0
       09994.263                       0
Bank Sta=9597.045,10559.09
Exp/Cntr=0.3,0.1

Type RM Length L Ch R = 1 ,  5742.6,779.299100,779.299100,779.299100
XS GIS Cut Line= 2
919693.067638462826624.613485103920071.539860685825162.807929548
#Sta/Elev= 30
9127.49589.145769189.07486.610399220.06379.589599261.38279.955519302.70175.58277
9540.28575.202989560.94473.682569591.93368.703959612.59369.428799622.92268.19838
9664.24172.088619695.23169.43876 9715.8970.941989767.53969.979039881.16671.81692
9943.14469.391349963.80370.61228 10067.169.2189410077.4370.0551610087.7675.92814
10098.0984.5845810108.4285.32209   1034683.6899410480.2979.5025610521.61 79.9876
10573.2684.2425910583.5986.3820810604.2591.7747610624.91101.5079 10637.5105.0017
#Mann= 3 , 0 , 0
9127.495  0.0454       09127.495  0.0454       0 10637.5  0.0454       0
#XS Ineff= 2 , 0
       0 9495.24                       0
Bank Sta=9127.495,10637.5
Exp/Cntr=0.3,0.1

Type RM Length L Ch R = 1 ,4963.301,724.594700,724.594700,724.594700
XS GIS Cut Line= 2
919793.762082907826746.141262881920484.734305129826145.446818436
#Sta/Elev= 30
9580.41387.047519597.395 87.66379621.80586.839579714.55987.501649749.81486.05451
9780.81187.51041 9795.5485.239689807.31380.206389826.02470.841979841.26667.70058
9847.06467.332939873.56569.768429900.06669.643629917.47564.338869939.81862.86597
9963.20162.47032 9992.8263.5078410008.9365.2979710032.5766.6914210085.1468.07541
10130.8667.5057710138.5868.4189510151.8372.5729210176.5976.1286810191.8380.86077
10207.0784.5780110237.5685.2376110297.5884.7265410337.3383.7818810495.9982.04369
#Mann= 3 , 0 , 0
9580.413  0.0422       09580.413  0.0422       010495.99  0.0422       0
#XS Ineff= 2 , 0
       09875.007                       0
Bank Sta=9580.413,10495.99
Exp/Cntr=0.3,0.1

Type RM Length L Ch R = 1 ,4238.706,0.000000,0.000000,0.000000
XS GIS Cut Line= 2
920505.567638462827305.169040659920543.762082907826315.585707325
#Sta/Elev= 30
 9659.4178.886329769.66177.996069939.78879.844369949.79578.866839959.80369.13186
 9969.8160.673999979.81858.7247410009.8457.6722710029.8558.3684910049.8761.37005
10069.8861.2621310079.8963.8881210149.9461.2182110179.9761.71878   1022065.34423
10260.0366.4660110300.0665.1748810370.1165.6640910400.1364.4146910430.1564.79046
10460.1866.5629210470.1868.6788710480.1972.95368 10490.2 80.1504 10500.284.17363
10510.2184.5851710530.2383.2991810550.2485.0963510570.2683.1661110649.7382.80185
#Mann= 3 , 0 , 0
 9659.41    0.04       0 9659.41    0.04       010649.73    0.04       0
#XS Ineff= 2 , 0
       0                               0
Bank Sta=9659.41,10649.73
Exp/Cntr=0.3,0.1